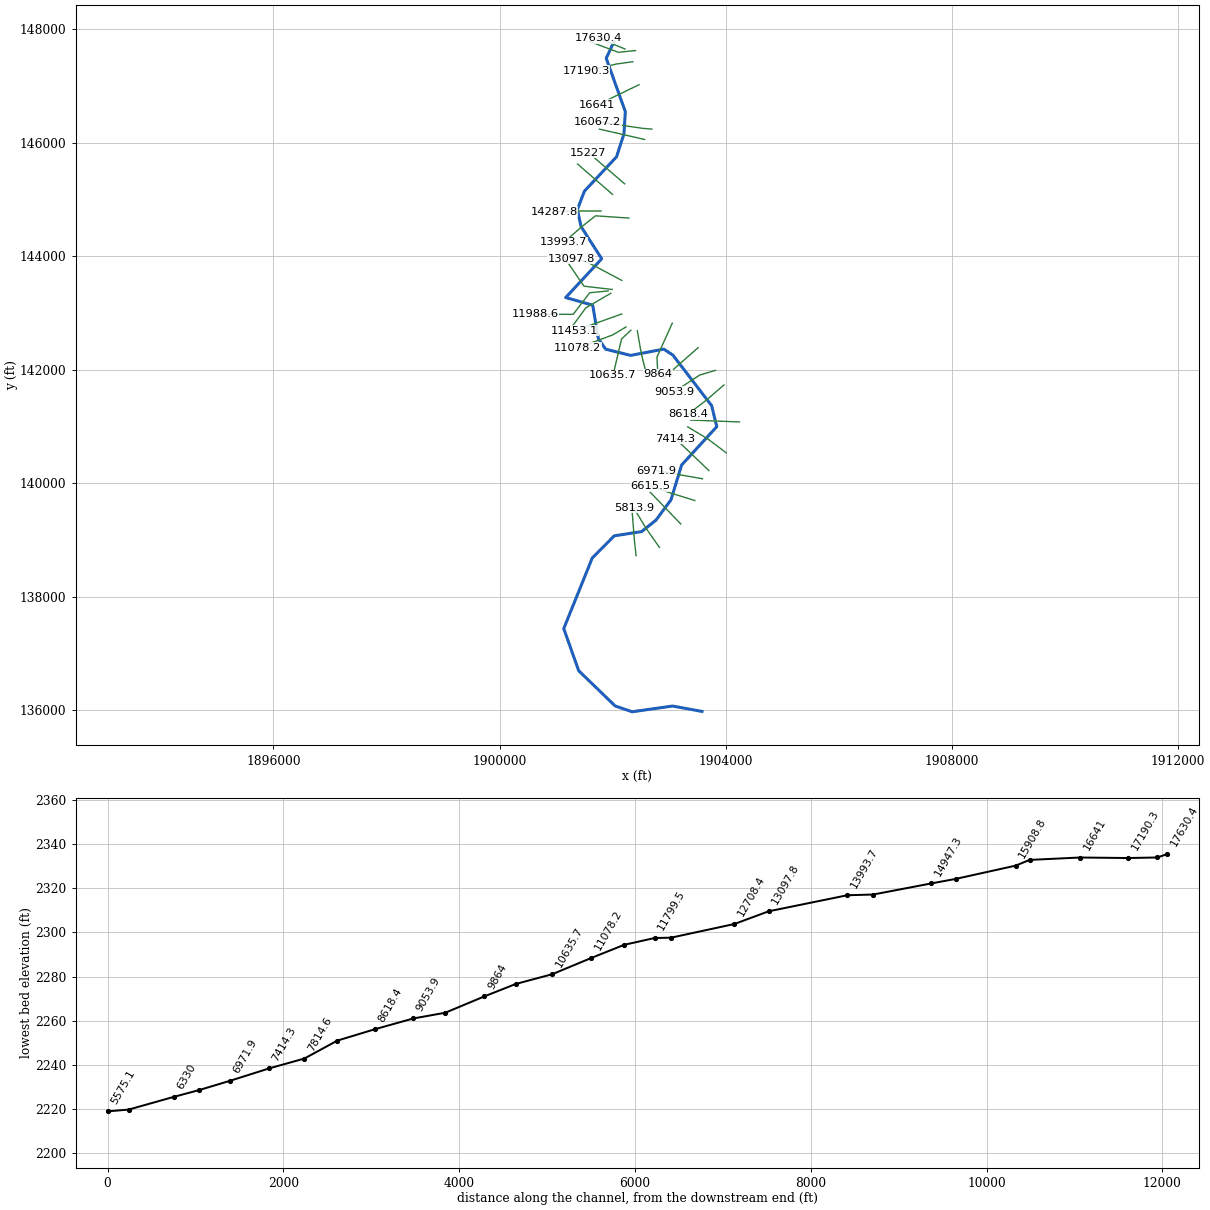
--- WdmthCrk.prj (project) ---

Proj Title=WdmthCrk
Current Plan=p01
Default Exp/Contr=0,0
English Units
Geom File=g01
Flow File=f01
Plan File=p01
BEGIN DESCRIPTION:
END DESCRIPTION:
DSS Export Rating Curves= 0
DSS Export Rating Curve Sorted= 0
DSS Export Volume Flow Curves= 0
DXF OffsetX= 0
DXF OffsetY= 0
DXF ScaleX= 0
DXF ScaleY= 0

--- WdmthCrk.p01 (plan) ---

Plan Title=Floodplain
Program Version=4.00
Geom File=g01
Flow File=f01
K Sum by GR=0
Std Step Tol=0.01
Critical Tol=0.01
Num of Std Step Trials=20
Max Error Tol=0.3
Flow Tol Ratio=0.001
Split Flow NTrial=30
Split Flow Tol=0.02
Split Flow Ratio=0.02
Log Output Level=0
Friction Slope Method=1
Unsteady Friction Slope Method=2
Unsteady Bridges Friction Slope Method=1
Global Log Level=0
CheckData=False
Run HTab=0
Run UNet=0
Run PostProcess=0
UNET Theta=0
UNET Theta Warmup=0
UNET ZTol=0
UNET ZSATol=0
UNET MxIter=0
UNET MaxInSteps=0
UNET DtIC=0
UNET DtMin=0
UNET MaxCRTS=0
UNET WFStab=0
UNET SFStab=0
UNET WFX=0
UNET SFX=0
UNET DSS MLevel=0
UNET DZMax Abort=0
UNET Convert EG Bridges=0
UNET Use Existing IB Tables=0
UNET Froude Limit=0
UNET Froude Power=0
Write IC File=0
Echo Input=False
Echo Output=False
Write Detailed=0

--- WdmthCrk.f01 (steady flow) ---

Flow Title=NFF Regression Equation
Program Version=4.00
Number of Profiles=1
Profile Names=P100yr
River Rch & RM=WdmthCrk,Main      ,17630.4
3249.667
River Rch & RM=WdmthCrk,Main      ,6615.5
3464.778
River Rch & RM=WdmthCrk,Main      ,547.1
3842.874
Boundary for River Rch & Prof#=WdmthCrk,Main      ,1
Up Type=0
Dn Type=3
Dn Slope=0.002002

--- WdmthCrk.g01 (geometry) ---

Geom Title=USGS 3m DEM
Program Version=4.10

River Reach=WdmthCrk        ,Main
Reach XY= 30
     1902019.531      147772.318     1901885.728      147485.593
     1902223.585      146545.426     1902199.571      146155.876
     1902068.832      145750.318     1901500.214      145145.059
     1901375.942      144820.924     1901440.945       144520.89
     1901805.607      143953.577     1901169.221       143270.94
     1901646.776      143136.028     1901747.036      142546.184
     1901875.942      142361.288     1902318.651      142251.913
     1902904.588       142362.59     1903064.744      142257.121
     1903749.598      141366.882      1903840.91      140996.559
     1903219.233      140321.502     1903029.879      139705.607
      1902765.06       139350.01     1902512.564      139148.437
     1902028.187      139073.379     1901639.227      138683.992
     1901135.057      137439.413      1901399.38      136697.226
     1902042.595      136077.611     1902343.207      135974.443
     1903060.266      136075.572      1903579.35       135980.54

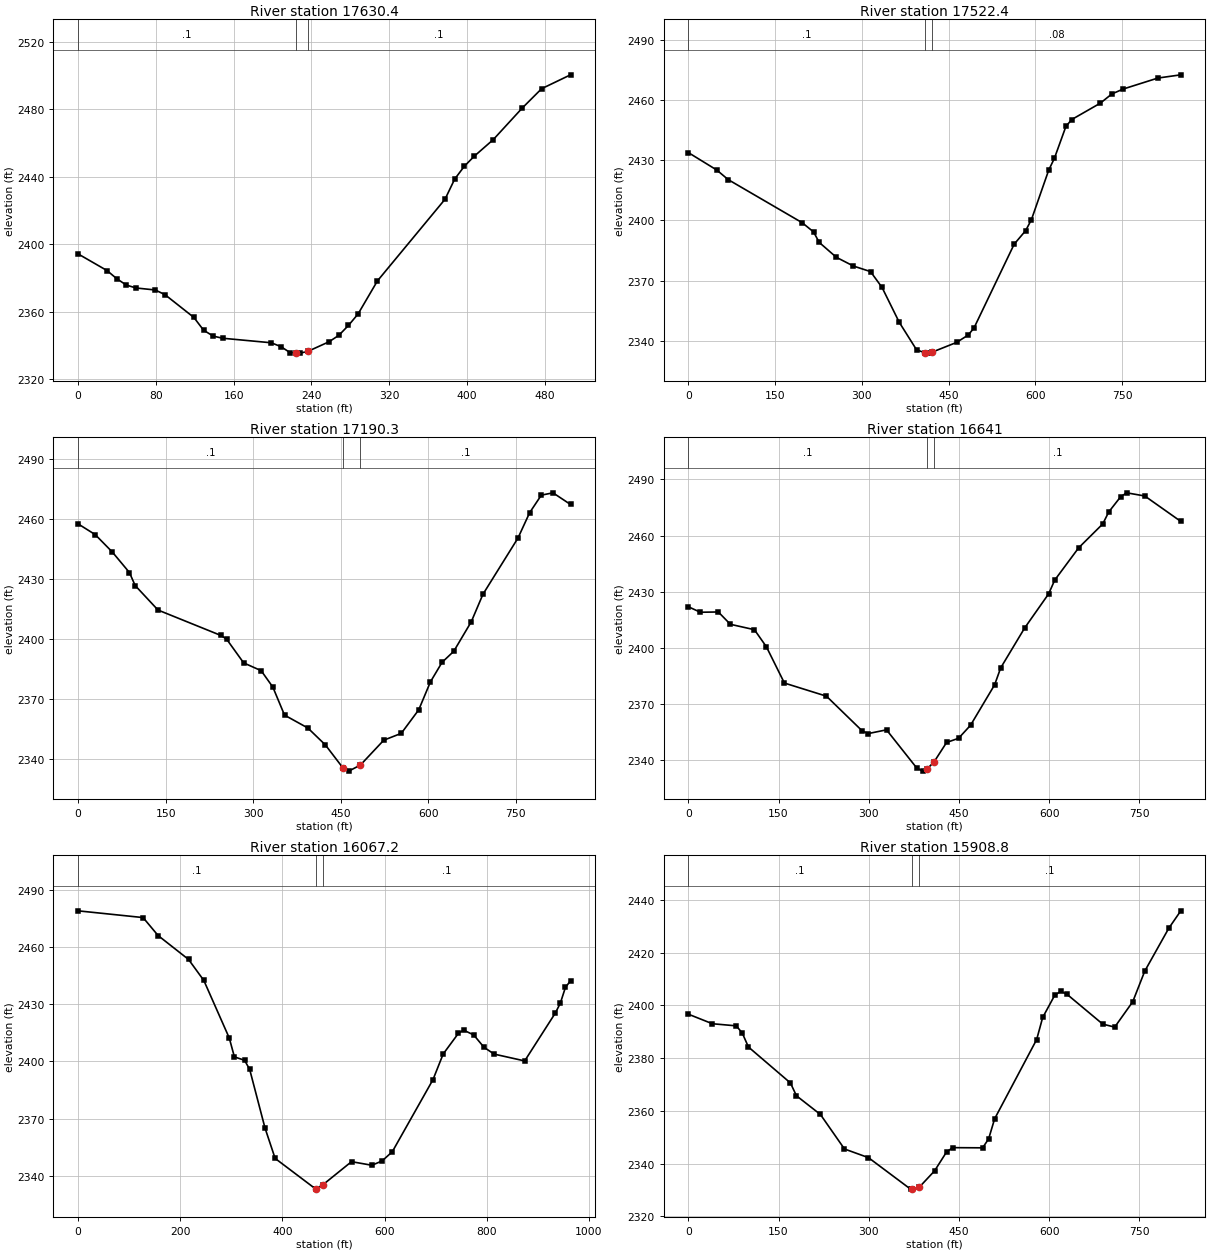
Type RM Length L Ch R = 1 ,17630.4 ,107.9,108,108.1
XS GIS Cut Line= 2
     1902219.788      147648.941     1901750.088      147838.061
#Sta/Elev= 30
       0 2394.31    29.8 2384.42    39.7 2379.65    49.6 2375.83    59.6  2374.1
    79.4 2372.91    89.4 2370.14   119.1 2356.63   129.1 2349.06     139 2345.56
   148.9  2344.3   198.6 2341.63   208.5 2339.37   218.4 2335.64   224.4 2335.55
   228.4 2335.49   236.4 2336.56   258.1 2342.24   268.1 2346.03     278  2351.9
   287.9  2358.7   307.8  2378.3   377.3 2426.69   387.2 2438.61   397.1  2446.2
   407.1 2452.06   426.9 2462.04   456.7 2480.75   476.6  2492.2   506.3 2500.42
#Mann= 3 , 0 , 0
       0      .1       0   224.4    .045       0   236.4      .1       0
Bank Sta=224.4,236.4
XS Rating Curve= 0 ,0
Exp/Cntr=0.3,0.1

Type RM Length L Ch R = 1 ,17522.4 ,319.9,331.9,343.8
XS GIS Cut Line= 3
      1902403.63      147621.393      1902100.15       147590.35
     1901588.858      147783.023
#Sta/Elev= 30
       0 2433.77    49.2 2425.08    68.9 2420.32   196.8 2398.88   216.5 2394.29
   226.3 2389.07   255.9 2381.66   285.4 2377.31     315 2374.54   334.9 2366.66
   364.7 2349.29   394.5 2335.66   409.2 2334.09   414.3 2333.97   421.2 2334.42
     464 2339.33   483.9 2342.99   493.8 2346.44   563.4 2388.22   583.2 2394.93
   593.2 2400.42     623    2425   632.9 2430.94   652.8 2446.79   662.7 2450.18
   712.4 2458.38   732.2 2462.94   752.1 2465.42   811.7 2470.85   851.4 2472.46
#Mann= 3 , 0 , 0
       0      .1       0   409.2    .045       0   421.2     .08       0
Bank Sta=409.2,421.2
XS Rating Curve= 0 ,0
Exp/Cntr=0.3,0.1

Type RM Length L Ch R = 1 ,17190.3 ,544.9,549.3,553.7
XS GIS Cut Line= 3
      1902355.03      147424.506     1902074.016      147385.348
     1901527.588      147263.457
#Sta/Elev= 30
       0 2457.45    29.4 2452.07    58.7 2443.36      88  2433.1    97.8  2426.6
     137 2414.32   244.6 2401.62   254.4 2399.79   283.7 2387.88   313.7 2383.98
   333.7 2375.77   353.7 2361.75   393.7 2355.29   423.7 2346.83   453.7 2335.36
   463.7 2333.72   483.7 2336.76   523.7  2349.2   553.7 2352.62   583.6  2364.4
   603.6 2378.36   623.6 2388.17   643.6 2393.68   673.6 2408.46   693.6 2422.21
   753.6 2450.34   773.6 2463.03   793.6 2471.81   813.6 2472.97   843.6 2467.15
#Mann= 3 , 0 , 0
       0      .1       0   453.7    .045       0   483.7      .1       0
Bank Sta=453.7,483.7
XS Rating Curve= 0 ,0
Exp/Cntr=0.3,0.1

Type RM Length L Ch R = 1 ,16641   ,586.4,573.8,561.3
XS GIS Cut Line= 3
     1902466.438       147020.37     1902097.662      146842.341
     1901728.885      146664.312
#Sta/Elev= 30
       0  2421.9      20 2418.96    49.9  2419.1    69.9 2412.51   109.9 2409.62
   129.8  2400.5   159.8 2381.07   229.7 2374.05   289.6 2355.34   299.6 2354.07
   329.6 2356.04   379.5 2335.77   389.5 2333.95     397 2335.04     409 2339.05
   429.5 2349.28   449.4 2351.52   469.4 2358.52   509.4 2380.14   519.4 2389.15
   559.3 2410.52   599.3 2428.84   609.3 2436.13   649.2 2453.45   689.2  2466.2
   699.2 2472.62   719.1  2480.8   729.1 2482.85   759.1 2481.16     819 2467.56
#Mann= 3 , 0 , 0
       0      .1       0     397    .045       0     409      .1       0
Bank Sta=397,409
XS Rating Curve= 0 ,0
Exp/Cntr=0.3,0.1

Type RM Length L Ch R = 1 ,16067.2 ,160.2,158.4,156.7
XS GIS Cut Line= 3
     1902692.587      146237.906      1902526.72      146251.858
     1901737.687       146366.57
#Sta/Elev= 30
       0 2479.23   127.3 2475.68   156.7 2466.23   216.3 2453.65   246.2  2442.6
     296 2412.32     306 2402.42   325.9 2400.63   335.9 2395.84   365.8 2365.11
   385.7 2349.03   465.4 2332.87   466.5 2333.02   478.5 2335.02   535.2 2347.31
   575.1 2345.42     595 2347.69     615 2352.52   694.7 2390.48   714.6 2403.94
   744.5 2414.83   754.5  2416.5   774.4 2413.95   794.4 2407.48   814.3 2403.88
   874.1 2400.29   933.9  2425.4   943.8 2430.61   953.8 2438.91   963.8 2442.48
#Mann= 3 , 0 , 0
       0      .1       0   466.5    .045       0   478.5      .1       0
Bank Sta=466.5,478.5
XS Rating Curve= 0 ,0
Exp/Cntr=0.3,0.1

Type RM Length L Ch R = 1 ,15908.8 ,691.9,681.6,671.4
XS GIS Cut Line= 3
     1902564.156      146055.315     1902165.077      146147.104
     1901765.545      146236.933
#Sta/Elev= 30
       0  2396.7      40 2393.07    79.9 2392.26    89.9 2389.45    99.9 2384.25
   169.8 2370.59   179.8 2365.72   219.7 2358.61   259.7 2345.51   299.6 2342.22
   369.6 2330.27   371.8 2330.28   383.8 2330.93   409.5  2337.2   429.5 2344.39
   439.5 2346.02   489.4 2345.95   499.4 2349.33   509.4 2356.97   579.3 2387.07
   589.3 2395.44   609.3 2403.87   619.2 2405.36   629.2 2404.36   689.2 2392.92
   709.1 2391.79   739.1 2401.43   759.1 2413.06     799 2429.32     819 2435.94
#Mann= 3 , 0 , 0
       0      .1       0   371.8    .045       0   383.8      .1       0
Bank Sta=371.8,383.8
XS Rating Curve= 0 ,0
Exp/Cntr=0.3,0.1

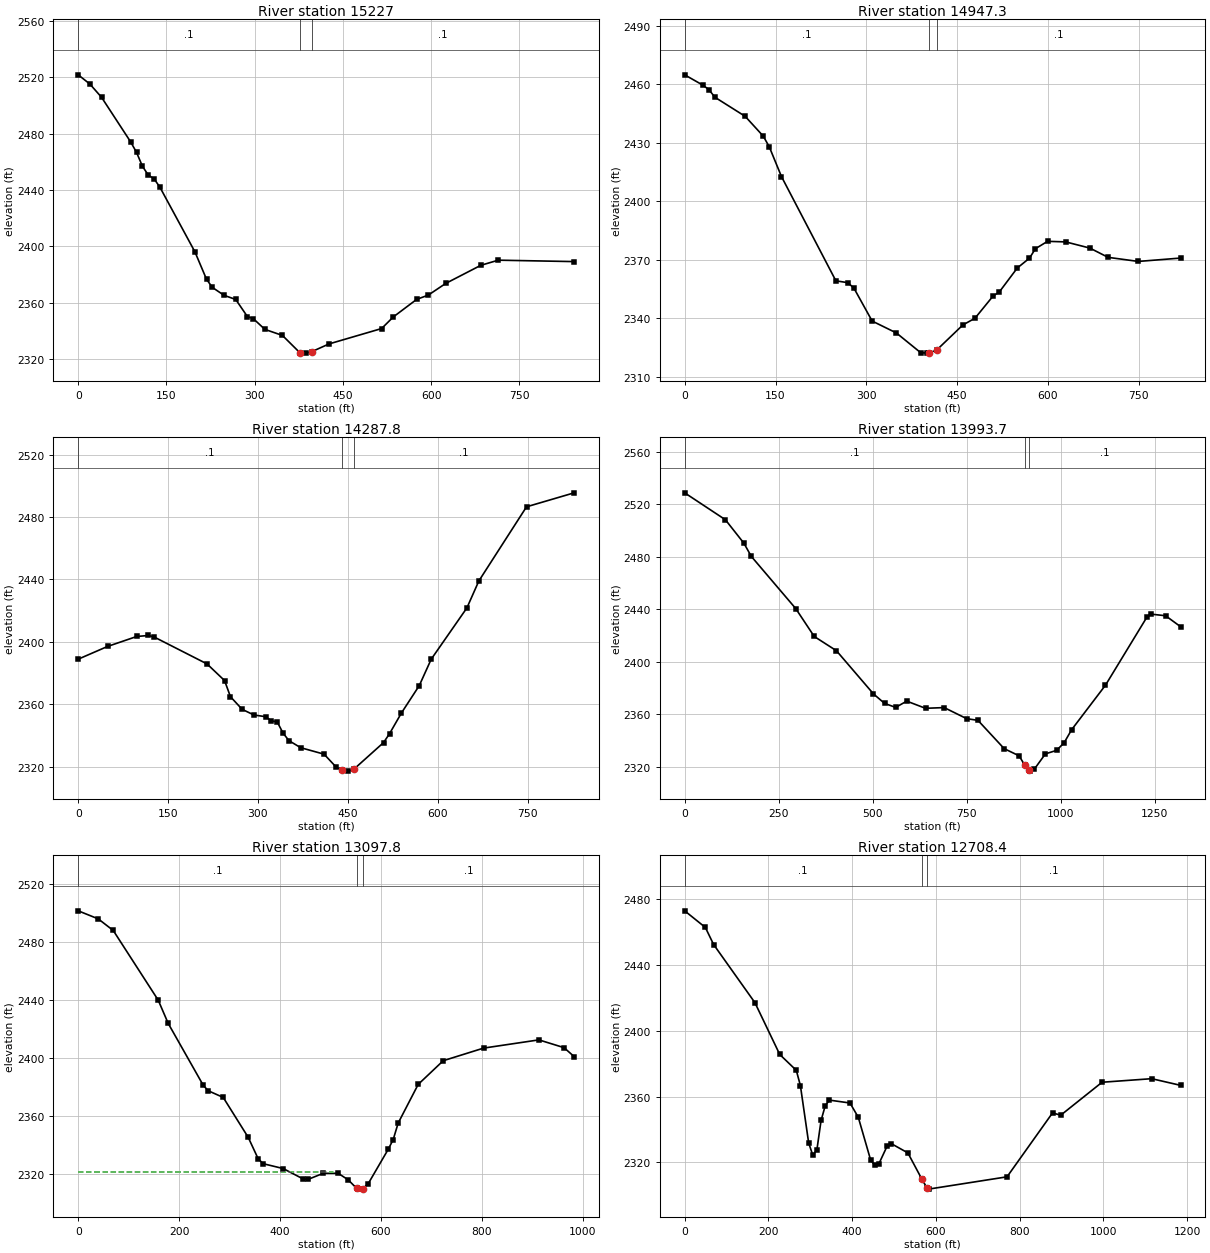
Type RM Length L Ch R = 1 ,15227   ,280,279.8,279.7
XS GIS Cut Line= 2
     1902212.037      145273.706      1901571.82      145822.463
#Sta/Elev= 30
       0 2521.83    19.8  2515.3    39.7 2505.86    89.3 2474.13    99.2 2466.73
   109.1    2457     119  2450.7     129    2448   138.9 2442.05   198.4 2396.18
   218.2 2376.64   228.2 2370.87     248 2365.29   267.8 2362.35   287.7 2350.19
   297.6 2348.77   317.4 2341.11   347.2 2336.83     377  2324.5   386.9 2324.26
   396.8 2325.25   426.6 2330.82   515.8 2341.71   535.7 2349.94   575.4 2362.41
   595.2 2365.45     625 2373.78   684.5  2386.6   714.2 2390.25   843.2 2389.24
#Mann= 3 , 0 , 0
       0      .1       0     377    .045       0   396.8      .1       0
Bank Sta=377,396.8
XS Rating Curve= 0 ,0
Exp/Cntr=0.3,0.1

Type RM Length L Ch R = 1 ,14947.3 ,644.5,659.4,674.9
XS GIS Cut Line= 3
     1901997.434      145087.709     1901687.855      145355.759
     1901378.275      145623.809
#Sta/Elev= 30
       0 2464.94      30 2459.65      40 2457.36    49.9 2453.44    99.9 2443.65
   129.8 2433.49   139.8 2427.94   159.8 2412.78   249.7 2359.28   269.7 2358.33
   279.7 2355.41   309.6 2338.65   349.6 2332.55   389.5 2322.49   399.5  2322.2
     404 2322.38     416 2323.73   459.4 2336.65   479.4 2340.09   509.4 2351.53
   519.4 2353.49   549.3 2365.87   569.3 2370.87   579.3 2375.78   599.3 2379.54
   629.2 2379.25   669.2 2376.07   699.2 2371.33   749.1 2369.23     819 2370.96
#Mann= 3 , 0 , 0
       0      .1       0     404    .045       0     416      .1       0
Bank Sta=404,416
XS Rating Curve= 0 ,0
Exp/Cntr=0.3,0.1

Type RM Length L Ch R = 1 ,14287.8 ,279.8,293.9,308.6
XS GIS Cut Line= 3
     1901793.736      144794.124     1901373.554      144795.986
     1900966.106      144784.344
#Sta/Elev= 30
       0 2388.93    48.9 2397.08    97.7 2403.48   117.3 2404.11     127 2403.09
     215 2385.89   244.3 2375.21   254.1 2364.88   273.6  2356.8   293.2 2353.16
   312.7 2352.08   322.5 2349.41   332.2 2348.71     342 2341.49   351.8 2336.71
   371.3 2332.21   410.4 2328.04   430.1 2319.94   440.1 2317.76     450 2317.18
     460 2318.38   509.7 2335.49   519.6 2341.15   539.5 2354.44   569.3 2372.01
   589.2 2388.91   648.8  2421.8   668.7 2439.04   748.3 2486.58   827.8 2495.54
#Mann= 3 , 0 , 0
       0      .1       0   440.1    .045       0     460      .1       0
Bank Sta=440.1,460
XS Rating Curve= 0 ,0
Exp/Cntr=0.3,0.1

Type RM Length L Ch R = 1 ,13993.7 ,921.6,895.3,872.6
XS GIS Cut Line= 4
     1902286.445      144670.693     1901697.433      144710.509
     1901446.804      144513.725     1901138.582      144244.301
#Sta/Elev= 30
       0 2528.68   108.2  2508.2   157.4 2490.34   177.1 2480.31   295.2  2440.6
   344.4 2419.35   403.4 2408.51   501.8 2375.66   531.3 2368.42   560.8 2365.37
   590.4 2370.13   640.2 2364.68   689.9 2365.22   749.7 2356.78   779.6 2355.52
   849.3 2333.98   889.1  2328.5   903.6 2321.58   915.6 2317.42     919 2316.86
     929 2318.15   958.9 2329.99   988.9 2332.68  1008.9 2338.55  1028.8 2348.45
  1118.7 2382.29  1228.5 2433.94  1238.5 2436.39  1278.4 2435.13  1318.4 2426.78
#Mann= 3 , 0 , 0
       0      .1       0   903.6    .045       0   915.6      .1       0
Bank Sta=903.6,915.6
XS Rating Curve= 0 ,0
Exp/Cntr=0.3,0.1

Type RM Length L Ch R = 1 ,13097.8 ,400.4,389.3,378.2
XS GIS Cut Line= 3
     1902160.881      143573.178     1901529.965      143906.463
     1901265.225      143956.535
#Sta/Elev= 30
       0 2501.55    39.6 2496.01    69.4 2488.01   158.6 2439.91   178.4 2423.87
   247.8 2381.23   257.7 2377.43   287.4 2372.84     337 2345.27   356.8 2330.42
   366.7 2327.11   406.3 2323.77     446 2316.56   455.9 2316.35   485.6 2320.47
   515.3  2320.5   535.2 2315.97     552 2310.08     555 2309.58     564 2309.91
   574.8 2313.32   614.4 2337.02   624.3 2343.74   634.2 2355.15   673.9 2381.84
   723.5 2398.16   803.4 2406.85   913.1 2412.53     963 2407.16     983 2400.98
#Mann= 3 , 0 , 0
       0      .1       0     552    .045       0     564      .1       0
#XS Ineff= 2 , 0
          505.42 2321.29
Permanent Ineff=
       F       F
Bank Sta=552,564
XS Rating Curve= 0 ,0
Exp/Cntr=0.3,0.1

Type RM Length L Ch R = 1 ,12708.4 ,681.1,719.6,758.8
XS GIS Cut Line= 3
     1901991.914      143413.253     1901491.728      143471.126
     1901107.288      144033.318
#Sta/Elev= 30
       0 2472.71    49.4 2462.62    69.1 2452.27   167.8 2416.97   227.1 2385.53
   266.6 2375.92   276.4 2366.67   296.2  2331.8   306.1 2324.36   315.9 2327.84
   325.8 2345.51   335.7  2354.4   345.6 2357.85   394.9 2356.09   414.7  2347.4
   444.3 2321.39   454.2  2318.4     464 2319.27   483.8 2330.07   493.6 2331.42
   533.1 2325.82   566.4 2309.95   578.4 2304.71   582.5 2303.83     770  2311.3
   878.6 2350.07   898.3  2348.7     997 2368.69  1115.5 2370.85  1184.6  2366.8
#Mann= 3 , 0 , 0
       0      .1       0   566.4    .045       0   578.4      .1       0
Bank Sta=566.4,578.4
XS Rating Curve= 0 ,0
Exp/Cntr=0.3,0.1

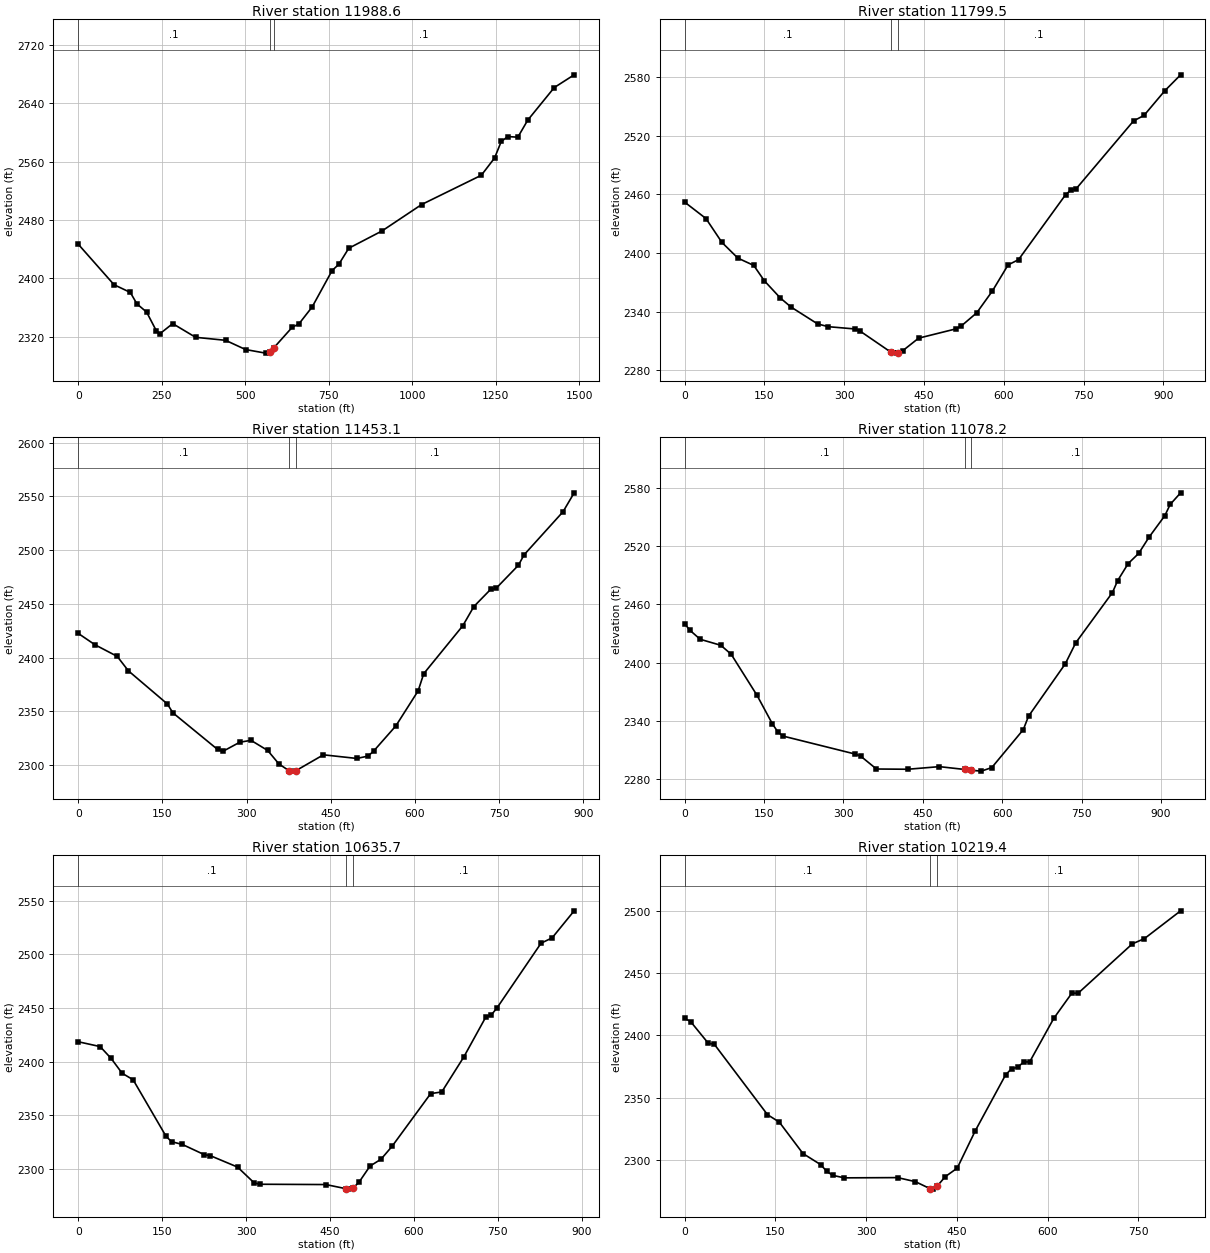
Type RM Length L Ch R = 1 ,11988.6 ,194.7,189.1,182.8
XS GIS Cut Line= 4
      1901922.96      143387.434     1901593.005       143355.38
     1901302.434      142975.511     1900627.771      142977.141
#Sta/Elev= 30
       0 2447.03   107.2 2391.45     156 2380.86   175.5  2365.3   204.8 2353.88
     234 2328.08   243.8 2323.96   282.8 2338.11   351.4 2319.33   441.1 2315.21
   500.9 2302.56   560.7 2297.64   573.3 2299.87   585.3 2304.84   640.4 2333.05
   660.3 2337.56   700.2 2360.92     760 2410.94   779.9 2419.39   809.8 2441.46
     909 2465.09    1028 2501.43  1206.6 2541.56  1246.3 2565.27  1266.2  2587.9
    1286 2594.62  1315.8 2593.73  1345.5 2617.13  1424.9 2661.82  1484.4 2679.26
#Mann= 3 , 0 , 0
       0      .1       0   573.3    .045       0   585.3      .1       0
Bank Sta=573.3,585.3
XS Rating Curve= 0 ,0
Exp/Cntr=0.3,0.1

Type RM Length L Ch R = 1 ,11799.5 ,349.5,346.4,343.3
XS GIS Cut Line= 3
      1901967.84      143346.525     1901526.865      143090.819
       1901275.2       142751.09
#Sta/Elev= 30
       0 2451.91      40 2435.14      70 2410.74     100 2394.67   129.9 2387.18
   149.9 2371.39   179.9 2353.85   199.9 2344.63   249.9 2327.36   269.9 2324.52
   319.8  2322.2   329.8 2320.01   388.6 2298.12   399.8 2297.47   400.6 2297.66
   409.8 2299.84   439.8 2312.76   509.8 2322.25   519.6 2325.01   549.1 2338.69
   578.6 2361.05   608.1 2387.71   627.7 2393.06   716.2 2459.49   726.1 2464.24
   735.9 2465.46     844 2534.99   863.7 2540.63     903 2565.98   932.5 2582.14
#Mann= 3 , 0 , 0
       0      .1       0   388.6    .045       0   400.6      .1       0
Bank Sta=388.6,400.6
XS Rating Curve= 0 ,0
Exp/Cntr=0.3,0.1

Type RM Length L Ch R = 1 ,11453.1 ,374.1,374.4,374.8
XS GIS Cut Line= 2
     1902159.331      142981.274     1901326.533      142684.954
#Sta/Elev= 30
       0 2422.58    29.8 2412.01    69.5 2401.19    89.4 2387.75   158.9 2356.88
   168.8 2348.61   248.3 2314.59   258.2 2312.89     288 2321.29   307.9 2323.03
   337.7 2313.62   357.6 2301.13   375.6 2294.79   377.4 2294.38   387.6 2294.67
     437 2309.56   496.6 2306.18   516.5 2308.37   526.4 2312.95   566.1 2336.47
   605.8 2369.06   615.8 2385.07   685.3 2429.59   705.2  2447.6     735 2463.51
   744.9 2464.59   784.6 2486.01   794.6 2495.68   864.1 2535.81   883.9  2553.4
#Mann= 3 , 0 , 0
       0      .1       0   375.6    .045       0   387.6      .1       0
Bank Sta=375.6,387.6
XS Rating Curve= 0 ,0
Exp/Cntr=0.3,0.1

Type RM Length L Ch R = 1 ,11078.2 ,421.4,442.5,463.6
XS GIS Cut Line= 3
     1902236.491        142753.8     1902002.248      142613.369
     1901380.117      142381.878
#Sta/Elev= 30
       0 2440.17     9.8 2433.47    29.3 2424.16    68.3 2417.97    87.8 2408.77
   136.6 2366.51   165.8 2336.99   175.6 2329.13   185.3 2324.56   322.6 2305.91
   332.6 2303.79   362.3 2290.59   421.7 2290.35   481.2 2293.03   529.1 2290.11
   541.1 2289.28   560.4 2288.41   580.2 2292.08   639.7 2331.14   649.6 2344.97
     719 2398.88   738.8 2420.55   808.1 2472.28     818 2484.61   837.8  2502.1
   857.7  2512.6   877.5  2529.5   907.2 2551.54   917.1 2562.96   936.9 2574.96
#Mann= 3 , 0 , 0
       0      .1       0   529.1    .045       0   541.1      .1       0
Bank Sta=529.1,541.1
XS Rating Curve= 0 ,0
Exp/Cntr=0.3,0.1

Type RM Length L Ch R = 1 ,10635.7 ,407.6,416.2,426.3
XS GIS Cut Line= 3
      1902321.94      142695.168     1902157.264      142541.028
     1902005.033      141898.147
#Sta/Elev= 30
       0 2418.48    39.2 2413.97    58.8 2402.94    78.5 2389.11    98.1 2383.04
   156.9 2330.39   166.7 2325.34   186.3  2322.7   225.6 2313.14   235.4 2312.43
   284.7 2301.65   314.3 2286.97   324.2 2285.64   442.5 2285.35   478.7 2281.46
   481.9 2281.09   490.7 2281.88   501.7 2287.51   521.4 2302.56   541.1 2308.99
   560.8 2320.97   629.8 2370.12   649.6 2371.68     689 2404.28   728.4 2441.58
   738.3 2443.58   748.2  2449.9   827.1 2510.38   846.8 2515.28   886.2 2540.52
#Mann= 3 , 0 , 0
       0      .1       0   478.7    .045       0   490.7      .1       0
Bank Sta=478.7,490.7
XS Rating Curve= 0 ,0
Exp/Cntr=0.3,0.1

Type RM Length L Ch R = 1 ,10219.4 ,368.6,355.4,340.8
XS GIS Cut Line= 3
     1902435.837      142686.742     1902506.621      142282.103
     1902605.885      141885.049
#Sta/Elev= 30
       0 2413.62     9.8 2411.03    39.1 2393.58    48.9 2392.88   136.9 2336.38
   156.5 2330.37   195.6 2305.18     225 2296.24   234.7 2290.99   244.5 2287.72
   264.1 2285.68   352.1 2285.88   381.4 2282.65   405.5 2277.08   410.8 2276.64
   417.5 2279.02   430.8 2286.59   450.7  2293.5   480.7 2323.58   530.6  2368.2
   540.6 2373.32   550.5 2374.26   560.5 2378.62   570.5  2378.7   610.4 2413.65
   640.4 2433.92   650.4 2433.66   740.2 2473.34   760.2 2477.54   820.1 2499.84
#Mann= 3 , 0 , 0
       0      .1       0   405.5    .045       0   417.5      .1       0
Bank Sta=405.5,417.5
XS Rating Curve= 0 ,0
Exp/Cntr=0.3,0.1

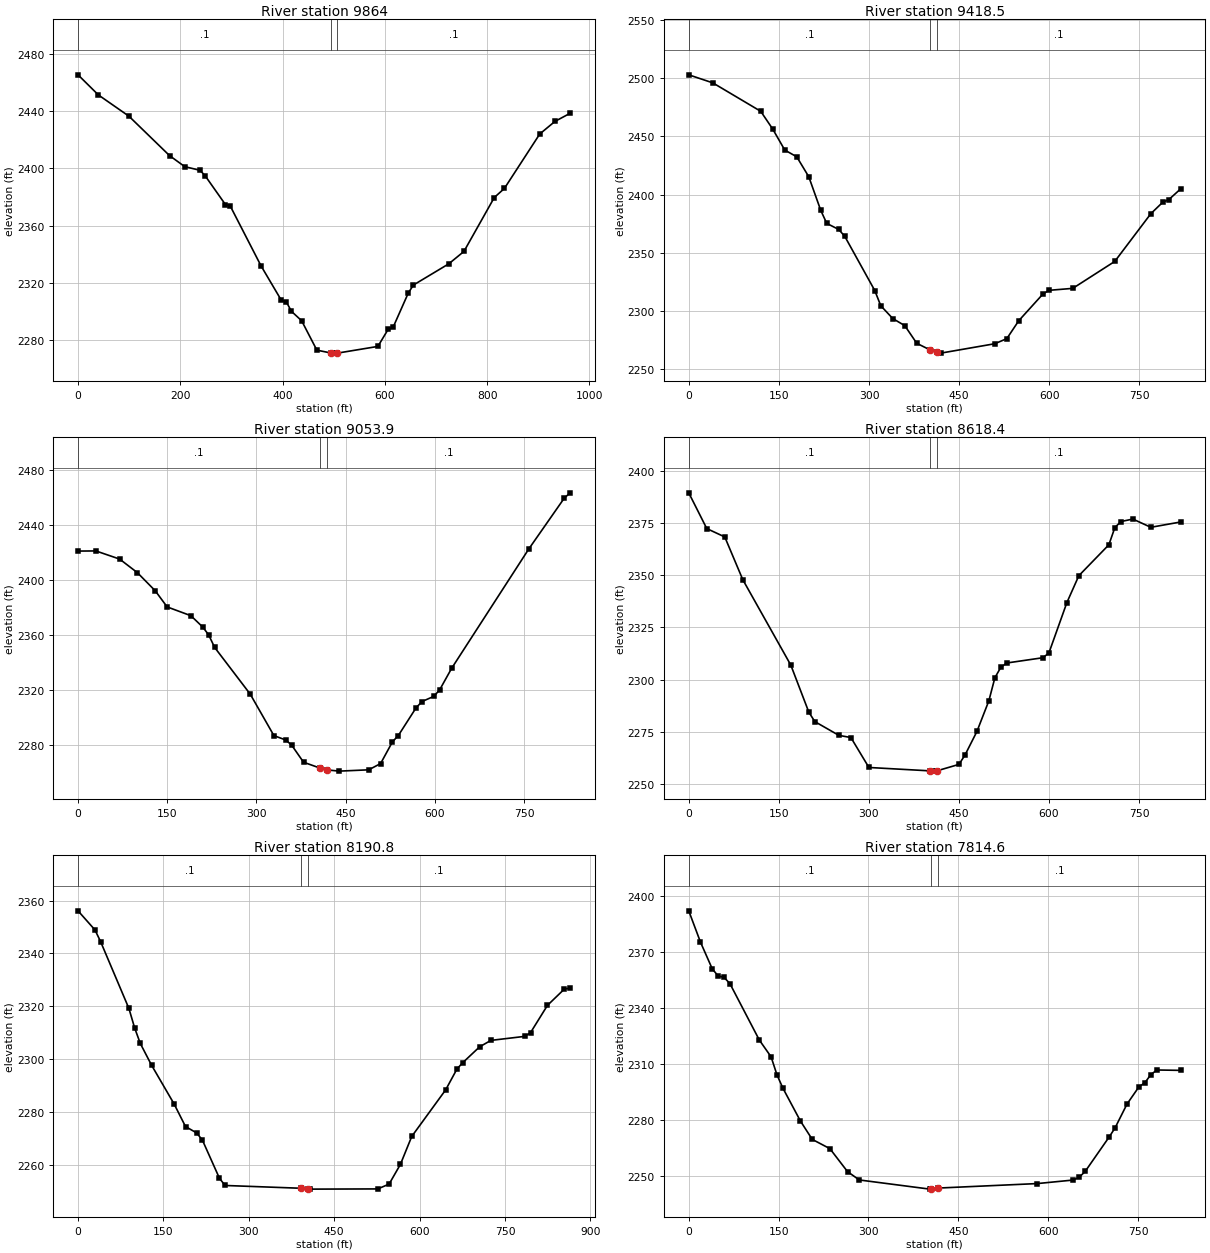
Type RM Length L Ch R = 1 ,9864    ,454.2,445.5,436.8
XS GIS Cut Line= 3
     1903054.291      142820.057      1902783.53      142222.728
     1902798.212      141916.807
#Sta/Elev= 30
       0 2465.13    39.8 2451.11    99.4 2436.32   178.9 2408.81   208.7 2401.09
   238.5 2398.55   248.4 2394.82   288.2 2374.66   298.1 2373.32   357.7 2331.99
   397.5 2307.91   407.4 2306.68   417.4 2300.15   437.2 2293.64     467 2273.11
   495.1  2271.1   506.8 2271.04   507.1 2271.04   586.3 2275.72   606.2 2287.53
   616.1 2289.08   645.9 2313.07   655.8 2318.53     725 2333.34   754.6 2341.98
   813.9 2379.56   833.7 2385.91   902.8 2423.86   932.5 2432.64   962.1 2438.29
#Mann= 3 , 0 , 0
       0      .1       0   495.1    .045       0   507.1      .1       0
Bank Sta=495.1,507.1
XS Rating Curve= 0 ,0
Exp/Cntr=0.3,0.1

Type RM Length L Ch R = 1 ,9418.5  ,367.5,364.5,361.6
XS GIS Cut Line= 3
     1903511.555       142388.93      1903203.71       142118.89
     1902895.865       141848.85
#Sta/Elev= 30
       0    2503      40  2496.1   119.8 2471.63   139.8 2456.32   159.8 2438.31
   179.8 2432.47   199.8 2415.31   219.7 2386.42   229.7 2375.22   249.7 2369.98
   259.7 2364.05   309.6 2317.49   319.6 2304.39   339.6 2293.36   359.6 2287.26
   379.5 2272.08   401.2 2266.52   413.2  2264.4   419.5 2263.63   509.4 2271.71
   529.4  2276.1   549.3 2291.52   589.3 2314.35   599.3 2317.63   639.2 2319.34
   709.1 2342.52   769.1 2383.55     789 2393.45     799 2395.66     819 2405.02
#Mann= 3 , 0 , 0
       0      .1       0   401.2    .045       0   413.2      .1       0
Bank Sta=401.2,413.2
XS Rating Curve= 0 ,0
Exp/Cntr=0.3,0.1

Type RM Length L Ch R = 1 ,9053.9  ,432.6,435.4,437
XS GIS Cut Line= 3
     1903817.751      141988.227     1903540.009      141906.495
     1903089.965      141612.405
#Sta/Elev= 30
       0 2421.29      30 2421.39    69.9 2415.47    99.8 2405.56   129.8 2392.36
   149.8 2380.62   189.7 2374.22   209.6 2365.98   219.6 2360.25   229.6 2351.14
   289.5 2317.07   329.3 2286.87   349.2 2283.69   359.2 2279.89   379.1  2267.5
   407.3 2263.16   419.3 2261.89   438.9 2261.02   488.6 2261.97   508.6 2266.53
   528.5 2282.34   538.4 2286.95   568.3 2307.17   578.2  2311.7   598.2  2315.5
   608.1  2320.4     628 2335.89   757.4 2422.63   817.2 2459.76   827.1 2463.71
#Mann= 3 , 0 , 0
       0      .1       0   407.3    .045       0   419.3      .1       0
Bank Sta=407.3,419.3
XS Rating Curve= 0 ,0
Exp/Cntr=0.3,0.1

Type RM Length L Ch R = 1 ,8618.4  ,443.4,427.6,412.9
XS GIS Cut Line= 3
     1903968.516      141732.115      1903657.94      141464.534
     1903332.393      141216.143
#Sta/Elev= 30
       0 2389.45      30 2372.33      60 2368.32      90 2347.85     170 2306.91
     200 2284.37     210 2279.87     250 2273.29     270 2272.25     300 2257.91
   401.5 2256.29     410 2256.16   413.5 2256.32   449.9 2259.38   459.9 2263.79
   479.9 2275.18   499.8 2289.89   509.8 2300.91   519.8 2305.94   529.8 2307.96
   589.7 2310.47   599.7 2312.72   629.7  2336.9   649.6 2349.77   699.6 2364.57
   709.6 2372.83   719.6 2375.68   739.5 2376.89   769.5 2372.94   819.4  2375.5
#Mann= 3 , 0 , 0
       0      .1       0   401.5    .045       0   413.5      .1       0
Bank Sta=401.5,413.5
XS Rating Curve= 0 ,0
Exp/Cntr=0.3,0.1

Type RM Length L Ch R = 1 ,8190.8  ,389.1,376.2,365.2
XS GIS Cut Line= 2
     1904241.994      141079.661     1903378.304       141112.67
#Sta/Elev= 30
       0  2356.1    29.8 2348.88    39.7 2344.45    89.4 2319.22    99.4 2311.92
   109.3 2306.05   129.2 2297.79   168.9 2283.11   188.8 2274.63   208.6  2272.2
   218.6 2269.45   248.4 2255.11   258.3 2252.38   391.2 2251.33   403.2 2251.09
   407.3    2251   526.5 2251.08   546.4  2252.9   566.3 2260.36   586.2  2270.9
   645.8  2288.5   665.6 2296.36   675.6 2298.72   705.4 2304.74   725.2 2307.17
   784.8 2308.69   794.8 2310.08   824.6 2320.41   854.4 2326.59   864.3 2326.87
#Mann= 3 , 0 , 0
       0      .1       0   391.2    .045       0   403.2      .1       0
Bank Sta=391.2,403.2
XS Rating Curve= 0 ,0
Exp/Cntr=0.3,0.1

Type RM Length L Ch R = 1 ,7814.6  ,403.7,400.3,394.8
XS GIS Cut Line= 3
     1904008.486      140535.866     1903678.423      140782.857
     1903327.309      140992.648
#Sta/Elev= 30
       0 2392.17    19.6 2375.34    39.3 2360.99    49.1 2357.23    58.9 2356.47
    68.7 2353.12   117.8 2322.84   137.4 2313.85   147.2 2304.22     157 2297.11
   186.5 2279.34   206.1 2269.55   235.6 2264.57     265 2252.26   284.6 2247.78
   402.4 2242.86   403.6 2242.91   415.6 2243.42   581.8 2245.84   641.7 2247.74
   651.7 2249.24   661.6 2252.32   701.6 2270.79   711.5 2275.68   731.5  2288.5
   751.4 2297.73   761.4 2299.99   771.4 2304.34   781.4 2306.78   821.3 2306.57
#Mann= 3 , 0 , 0
       0      .1       0   403.6    .045       0   415.6      .1       0
Bank Sta=403.6,415.6
XS Rating Curve= 0 ,0
Exp/Cntr=0.3,0.1

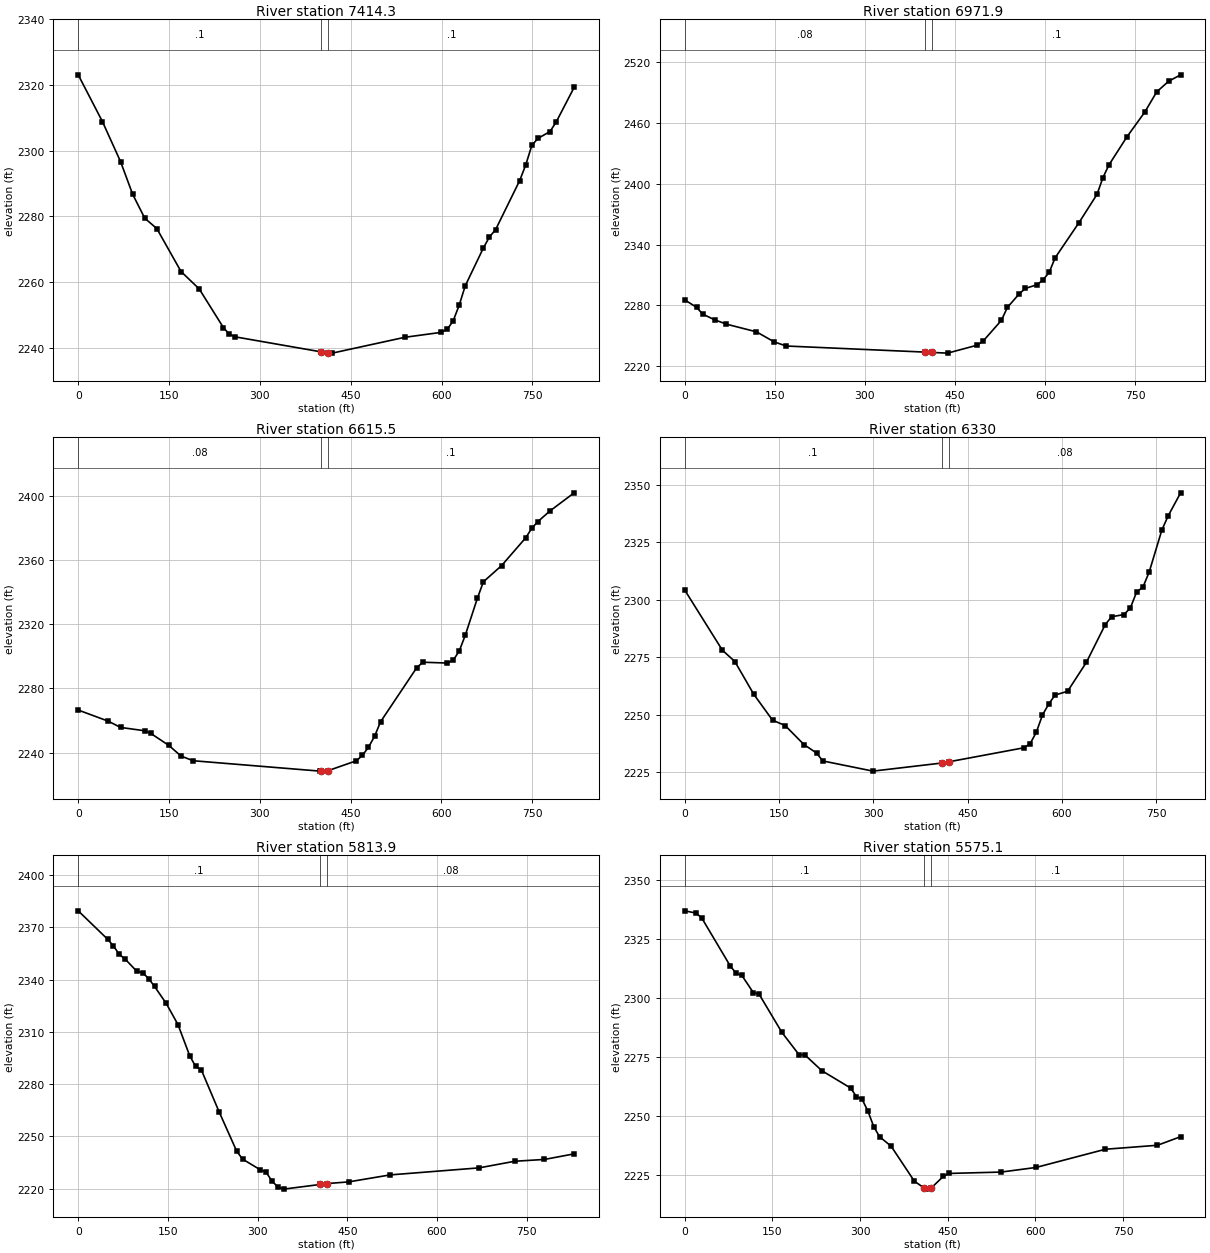
Type RM Length L Ch R = 1 ,7414.3  ,429.7,442.1,454.6
XS GIS Cut Line= 3
     1903701.261      140222.987     1903404.768      140505.445
     1903108.276      140787.903
#Sta/Elev= 30
       0 2323.13      40 2308.89    69.9 2296.72    89.9 2286.77   109.9 2279.47
   129.8 2276.32   169.8 2263.24   199.8 2257.95   239.7  2246.2   249.7  2244.1
   259.7 2243.34   401.3 2238.78   413.3 2238.51   419.5  2238.4   539.3 2243.22
   599.3 2244.72   609.3  2245.6   619.2 2248.22   629.2 2253.02   639.2 2258.92
   669.2 2270.46   679.2  2273.8   689.2 2275.97   729.1 2290.95   739.1 2295.73
   749.1 2301.64   759.1 2303.76     779 2305.85     789 2308.65     819 2319.31
#Mann= 3 , 0 , 0
       0      .1       0   401.3    .045       0   413.3      .1       0
Bank Sta=401.3,413.3
XS Rating Curve= 0 ,0
Exp/Cntr=0.3,0.1

Type RM Length L Ch R = 1 ,6971.9  ,359,356.3,353.2
XS GIS Cut Line= 2
     1903588.093      140079.072     1902774.672      140220.435
#Sta/Elev= 30
       0 2285.44    19.9    2278    29.8 2271.41    49.7 2265.76    69.6  2261.4
   119.4 2253.86   149.2 2243.86   169.1 2239.84   400.2 2233.83   412.2 2233.48
   437.7 2232.82   487.4 2240.74   497.4  2245.1   527.2 2265.13   537.2 2277.96
     557 2291.36     567 2296.68   586.9 2300.42   596.8 2305.28   606.8 2312.56
   616.7 2326.93   656.5 2361.73   686.4 2389.57   696.3 2406.07   706.2 2418.57
   736.1 2446.25   765.9 2470.76   785.8 2490.77   805.7 2501.27   825.6 2507.59
#Mann= 3 , 0 , 0
       0     .08       0   400.2    .045       0   412.2      .1       0
Bank Sta=400.2,412.2
XS Rating Curve= 0 ,0
Exp/Cntr=0.3,0.1

Type RM Length L Ch R = 1 ,6615.5  ,296,285.4,275.3
XS GIS Cut Line= 3
     1903453.766      139695.213     1903062.541      139816.143
     1902674.162      139947.048
#Sta/Elev= 30
       0 2266.56    49.9 2259.59    69.9 2255.75   109.9 2253.66   119.8 2252.04
   149.8 2244.54   169.8 2237.95   189.8 2235.03   399.5 2228.56   400.5 2228.56
   412.5 2228.82   459.5    2235   469.5 2238.36   479.5 2243.43   489.5 2250.15
   499.5 2259.27   559.4 2292.98   569.4  2296.3   609.4  2295.8   619.4 2297.47
   629.4 2303.24   639.4 2313.04   659.4 2336.06   669.4 2346.36   699.4  2356.4
   739.4 2373.77   749.4 2379.68   759.4  2383.8   779.4 2390.42   819.3 2401.68
#Mann= 3 , 0 , 0
       0     .08       0   400.5    .045       0   412.5      .1       0
Bank Sta=400.5,412.5
XS Rating Curve= 0 ,0
Exp/Cntr=0.3,0.1

Type RM Length L Ch R = 1 ,6330    ,518,515.1,510.4
XS GIS Cut Line= 2
     1903203.594      139282.357     1902656.244      139849.947
#Sta/Elev= 30
       0 2304.31    59.9 2278.12    79.8 2273.18   109.8 2258.96   139.7 2247.66
   159.7 2245.35   189.6 2237.08   209.6  2233.4   219.6 2229.94   299.4 2225.51
   408.7 2229.03   420.7  2229.6     539 2235.65     549 2237.34     559 2242.37
   568.9 2249.94   578.9 2254.74   588.9 2258.61   608.8 2260.24   638.8 2272.89
   668.7 2289.26   678.7 2292.65   698.7 2293.63   708.7 2296.58   718.6 2303.45
   728.6 2305.54   738.6  2312.2   758.6 2330.31   768.6 2336.51   788.5 2346.57
#Mann= 3 , 0 , 0
       0      .1       0   408.7    .045       0   420.7     .08       0
Bank Sta=408.7,420.7
XS Rating Curve= 0 ,0
Exp/Cntr=0.3,0.1

Type RM Length L Ch R = 1 ,5813.9  ,250.2,238.7,228.5
XS GIS Cut Line= 3
     1902825.879      138871.433     1902588.537      139208.472
     1902372.969      139565.567
#Sta/Elev= 30
       0 2379.46    49.1 2363.18    58.9 2359.32    68.7 2354.44    78.5 2351.76
    98.2 2344.66     108 2343.89   117.8 2340.55   127.6 2336.06   147.2 2326.31
   166.8 2314.19   186.5 2296.23   196.3 2290.15   206.1 2287.99   235.6 2264.11
     265 2241.51   274.8 2236.97   304.3 2230.87   314.1 2229.51   323.9 2224.43
   333.7    2221   343.5 2219.74   404.4 2222.41   416.4 2222.95     452 2223.88
   521.5  2227.9   670.4 2231.94     730 2235.74   779.7 2236.78   829.3 2239.98
#Mann= 3 , 0 , 0
       0      .1       0   404.4    .045       0   416.4     .08       0
Bank Sta=404.4,416.4
XS Rating Curve= 0 ,0
Exp/Cntr=0.3,0.1

Type RM Length L Ch R = 1 ,5575.1  ,202.1,212.1,222
XS GIS Cut Line= 3
      1902413.89      138724.732     1902384.953      138987.226
     1902338.529      139569.818
#Sta/Elev= 30
       0 2337.08    19.6 2336.12    29.3    2334    78.2 2313.58      88  2310.6
    97.8 2309.66   117.4 2302.39   127.2 2301.74   166.3 2285.48   195.6 2276.02
   205.4 2275.98   234.7 2269.21   283.9 2261.86   293.8 2258.24   303.7 2257.01
   313.6 2251.99   323.5 2245.44   333.4 2241.19   353.2 2237.17   392.9 2222.34
   409.2 2219.49   412.7 2218.94   421.2 2219.26   442.4 2224.34   452.3  2225.6
   541.4 2226.18   600.9 2228.13   719.8 2235.87   808.9 2237.56   848.5  2241.2
#Mann= 3 , 0 , 0
       0      .1       0   409.2    .045       0   421.2      .1       0
Bank Sta=409.2,421.2
XS Rating Curve= 0 ,0
Exp/Cntr=0.3,0.1