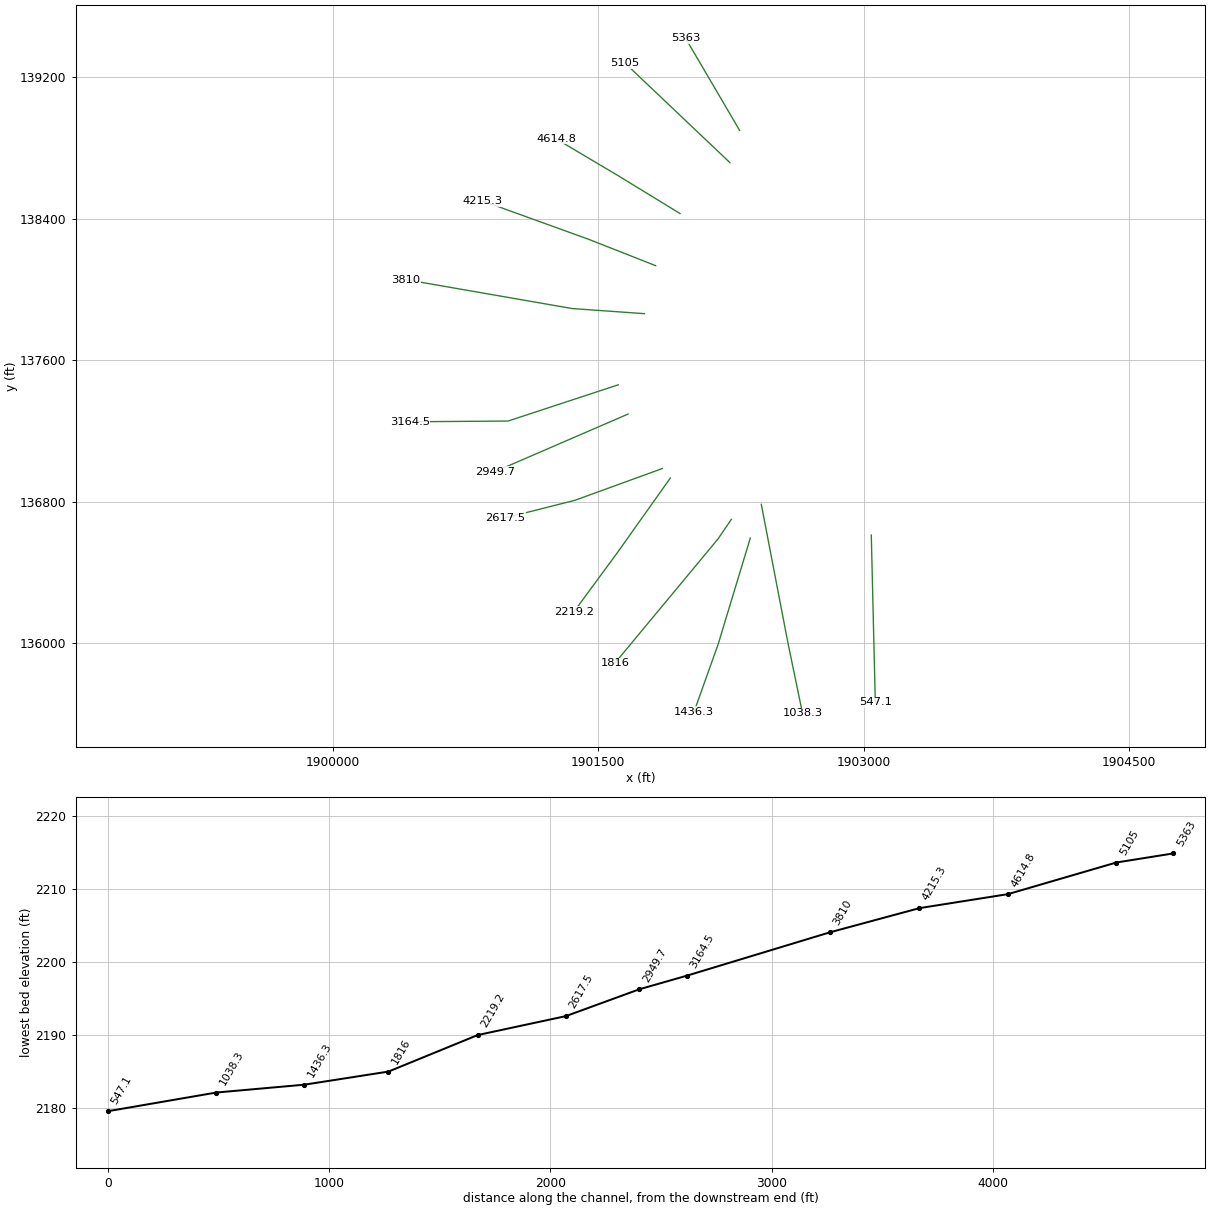
HEC-RAS study WdmthCrk.prj: WdmthCrk

--- WdmthCrk.g01 (geometry) --- (continued)

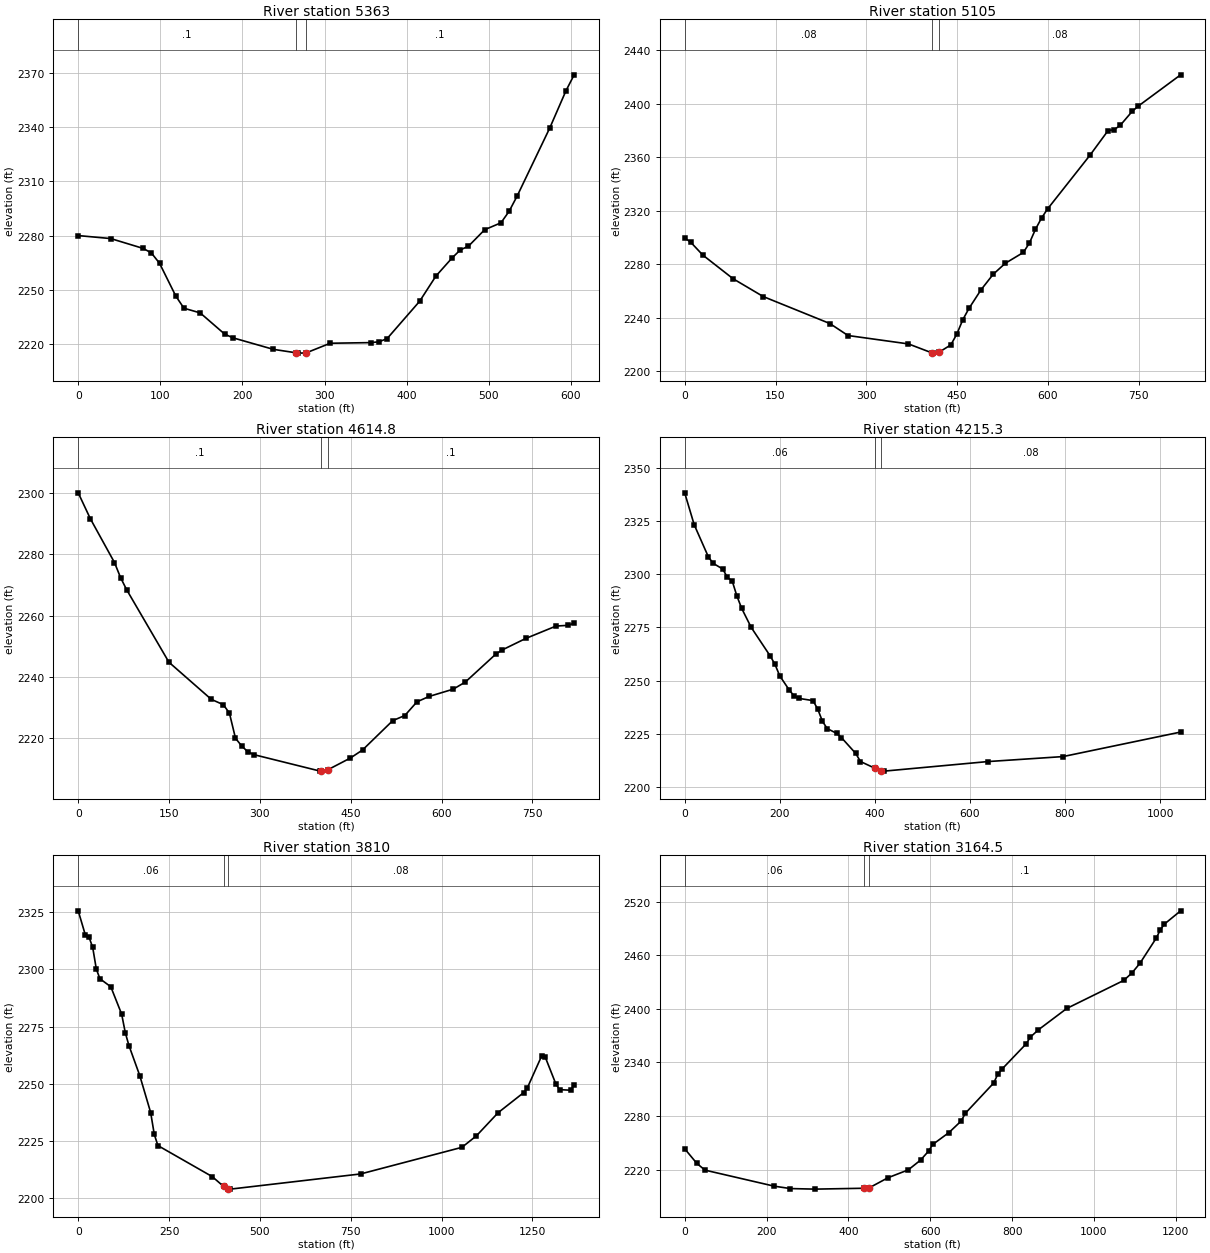
Type RM Length L Ch R = 1 ,5363    ,252.5,258,263.5
XS GIS Cut Line= 2
      1902299.19      138899.956     1901993.808      139420.811
#Sta/Elev= 30
       0    2280    39.6 2278.34    79.2 2272.87    89.1 2270.37      99 2264.67
   118.8 2246.53   128.7 2239.79   148.5 2237.19   178.2 2225.49   188.1 2223.43
   237.6 2217.01   265.2 2215.11   267.2 2214.92   277.2    2215   306.8 2220.39
   356.3 2220.74   366.2 2221.19   376.1 2222.97   415.7 2243.64   435.5 2257.58
   455.3 2267.67   465.2 2272.06   475.1 2274.12   494.9 2283.25   514.7 2287.07
   524.6 2293.43   534.5 2301.98   574.1 2339.56   593.9 2360.24   603.8 2368.99
#Mann= 3 , 0 , 0
       0      .1       0   265.2    .045       0   277.2      .1       0
Bank Sta=265.2,277.2
XS Rating Curve= 0 ,0
Exp/Cntr=0.3,0.1

Type RM Length L Ch R = 1 ,5105    ,485.7,490.1,494.8
XS GIS Cut Line= 3
     1902244.647      138717.391     1901947.571      138999.235
     1901650.495      139281.079
#Sta/Elev= 30
       0 2299.88      10 2296.58      30 2286.97    79.9 2269.31   129.8 2255.96
   239.7 2235.81   269.7 2226.84   369.6 2220.55   408.4 2213.85   409.5 2213.67
   420.4 2214.46   439.5 2219.81   449.4 2227.88   459.4 2238.74   469.4 2247.06
   489.4 2261.04   509.4 2272.59   529.4 2280.83   559.3 2288.96   569.3 2295.98
   579.3 2306.28   589.3 2314.68   599.3  2321.5   669.2  2361.6   699.2 2380.09
   709.1 2380.76   719.1  2383.9   739.1  2394.5   749.1 2398.41     819 2421.78
#Mann= 3 , 0 , 0
       0     .08       0   408.4    .045       0   420.4     .08       0
Bank Sta=408.4,420.4
XS Rating Curve= 0 ,0
Exp/Cntr=0.3,0.1

Type RM Length L Ch R = 1 ,4614.8  ,395.8,399.5,403.4
XS GIS Cut Line= 3
     1901961.633      138430.091     1901612.263      138643.788
     1901260.129        138852.8
#Sta/Elev= 30
       0 2299.98      20 2291.56    59.9 2277.27    69.9 2272.38    79.9 2268.44
   149.8  2244.8   219.8  2232.7   239.7 2230.96   249.7 2228.22   259.7 2220.05
   269.7 2217.57   279.7 2215.69   289.7 2214.71   399.6 2209.32   400.9 2209.35
   412.9 2209.83   449.5 2213.59   469.5  2216.2   519.4 2225.77   539.4 2227.44
   559.4 2231.89   579.3 2233.64   619.3 2236.02   639.3 2238.34   689.2 2247.36
   699.2  2248.7   739.1 2252.54   789.1 2256.58     809 2256.81     819 2257.54
#Mann= 3 , 0 , 0
       0      .1       0   400.9    .045       0   412.9      .1       0
Bank Sta=400.9,412.9
XS Rating Curve= 0 ,0
Exp/Cntr=0.3,0.1

Type RM Length L Ch R = 1 ,4215.3  ,398.8,405.2,409.3
XS GIS Cut Line= 3
     1901824.022      138134.985     1901442.675      138284.978
     1900846.861      138500.273
#Sta/Elev= 30
       0 2338.32      20 2323.32      50 2308.12      60 2305.15      80 2302.47
      90 2298.52     100 2296.83   109.9 2289.75   119.9 2283.96   139.9 2275.02
   179.9 2261.58   189.9 2257.66   199.9 2252.26   219.9 2245.58   229.9 2242.83
   239.9 2241.63   269.9 2240.58   279.8 2236.63   289.8 2230.86   299.8 2227.42
   319.8 2225.16   329.8 2223.16   359.8 2215.73   369.8 2211.92   400.9 2208.68
   412.9 2207.63   419.7  2207.4   637.4 2211.89   795.8 2214.24  1043.3 2225.78
#Mann= 3 , 0 , 0
       0     .06       0   400.9    .045       0   412.9     .08       0
Bank Sta=400.9,412.9
XS Rating Curve= 0 ,0
Exp/Cntr=0.3,0.1

Type RM Length L Ch R = 1 ,3810    ,637,645.4,655.8
XS GIS Cut Line= 3
     1901760.647      137863.409      1901352.86      137892.243
     1900410.749      138055.893
#Sta/Elev= 30
       0 2325.55    19.9 2314.86    29.9    2314    39.9 2309.57    49.8 2300.13
    59.8  2295.9    89.7  2292.4   119.6 2280.44   129.6 2272.33   139.6 2266.75
   169.5 2253.59   199.4  2237.5   209.4 2227.93   219.4 2223.08   368.9 2209.53
   400.2 2205.24   412.2 2204.31   418.8 2204.07   777.4  2210.7  1056.2 2222.32
  1096.1 2227.35  1155.8 2237.44  1225.6 2246.14  1235.5 2248.04  1275.4 2262.13
  1285.3 2261.75  1315.2 2249.76  1325.2  2247.5  1355.1 2247.24    1365 2249.43
#Mann= 3 , 0 , 0
       0     .06       0   400.2    .045       0   412.2     .08       0
Bank Sta=400.2,412.2
XS Rating Curve= 0 ,0
Exp/Cntr=0.3,0.1

Type RM Length L Ch R = 1 ,3164.5  ,212.9,214.8,216.8
XS GIS Cut Line= 3
     1901612.361      137460.901     1900989.476      137256.009
     1900433.484      137251.876
#Sta/Elev= 30
       0 2243.34    29.8 2226.89    49.7 2219.39   218.6 2201.44   258.3 2198.75
   317.9 2198.12     439 2199.11     451 2199.61   496.8 2210.89   546.4 2219.71
   576.2 2230.58   596.1 2240.79     606 2248.13   645.8 2261.51   675.6 2274.44
   685.5 2282.95     755 2316.99   764.9  2326.7   774.9 2332.36   834.4 2360.86
   844.4 2368.31   864.2 2376.55   933.7 2400.51  1072.7 2431.86  1092.6 2440.14
  1112.4  2451.1  1152.2 2479.28  1162.1 2488.56    1172 2494.93  1211.7 2509.81
#Mann= 3 , 0 , 0
       0     .06       0     439    .045       0     451      .1       0
Bank Sta=439,451
XS Rating Curve= 0 ,0
Exp/Cntr=0.3,0.1

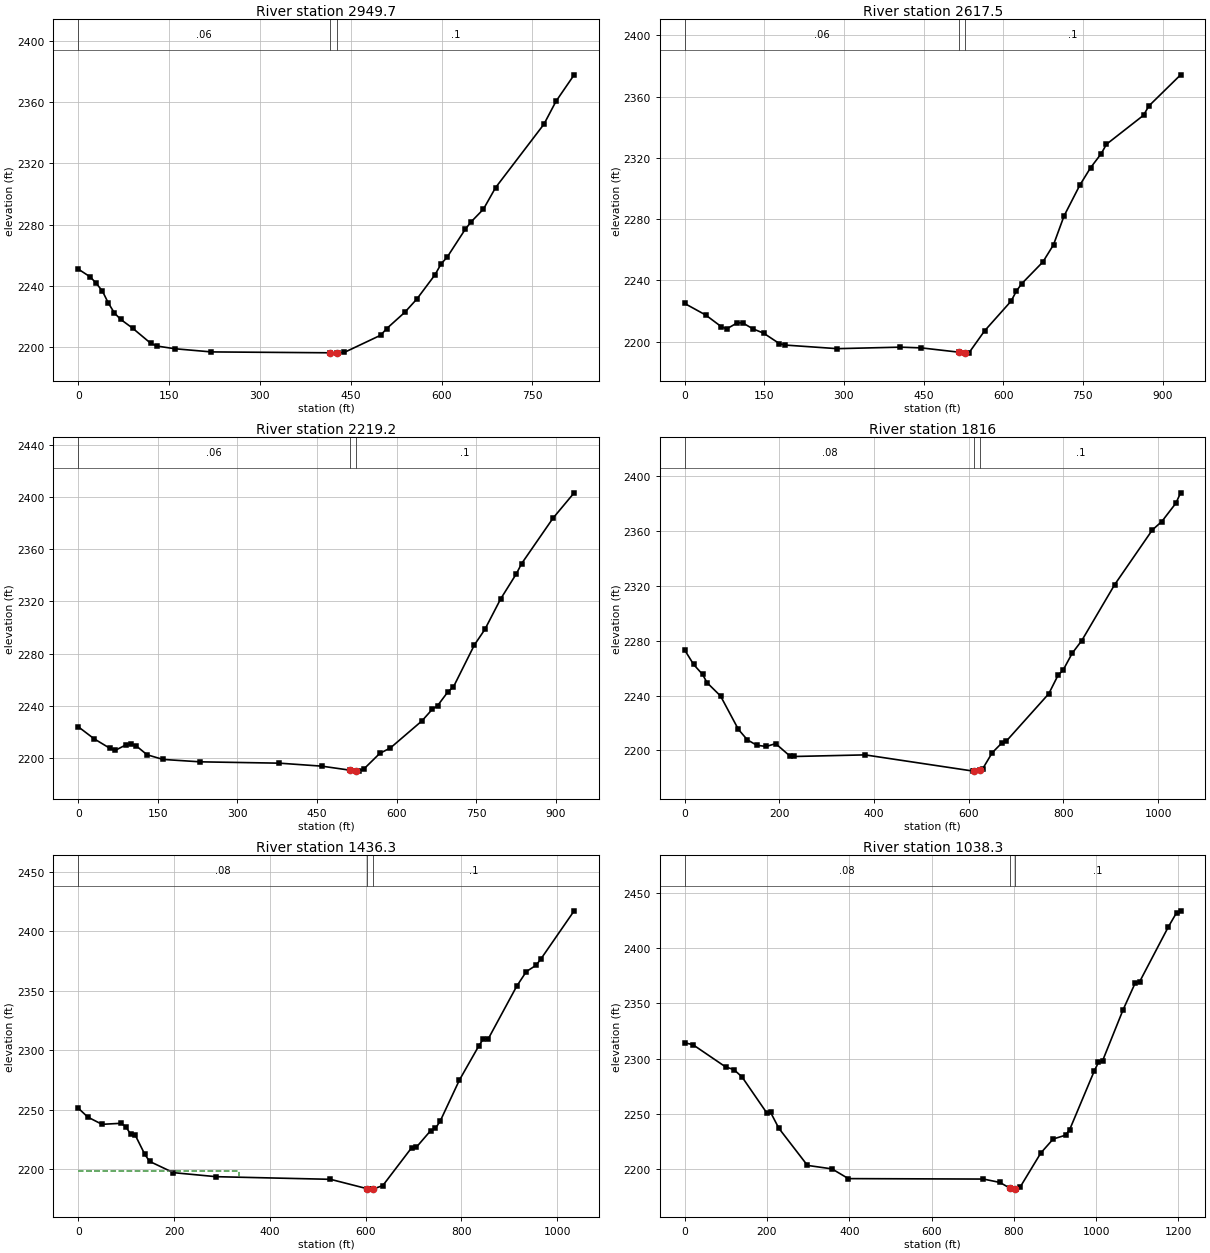
Type RM Length L Ch R = 1 ,2949.7  ,333.3,332.1,329.1
XS GIS Cut Line= 3
      1901668.55       137295.61     1901292.687      137133.075
     1900916.825       136970.54
#Sta/Elev= 30
       0 2251.05      20 2245.88      30 2241.65      40 2236.65    49.9 2228.77
    59.9 2222.36    69.9 2218.31    89.9 2212.49   119.8 2202.64   129.8 2200.88
   159.8  2199.1   219.7 2197.04     415 2196.47     427 2196.29   429.5 2196.25
   439.5 2196.73   499.4 2207.91   509.4 2212.23   539.3 2222.85   559.3 2231.54
   589.3 2247.37   599.3 2254.44   609.3  2258.8   639.2    2277   649.2 2281.96
   669.2 2290.09   689.2  2304.1   769.1 2345.45     789 2360.37     819 2377.63
#Mann= 3 , 0 , 0
       0     .06       0     415    .045       0     427      .1       0
Bank Sta=415,427
XS Rating Curve= 0 ,0
Exp/Cntr=0.3,0.1

Type RM Length L Ch R = 1 ,2617.5  ,385.2,398.1,412.4
XS GIS Cut Line= 3
       1901861.7      136987.315     1901368.318      136807.857
     1900971.824      136707.643
#Sta/Elev= 30
       0 2224.99    39.6 2217.44    69.3 2209.75    79.2  2208.4    99.1 2212.35
     109 2212.36   128.8 2208.36   148.6 2205.62   178.3 2198.79   188.2 2197.85
   287.3 2195.48   406.1 2196.46   445.8 2195.98     516 2193.19     528 2192.64
     535 2192.56   564.9 2207.14   614.8 2226.55   624.8 2233.13   634.7 2237.89
   674.6  2252.1   694.6 2263.31   714.5 2282.16   744.4 2302.38   764.4 2313.62
   784.4 2322.78   794.3 2328.94   864.2 2347.89   874.1 2353.93     934 2374.29
#Mann= 3 , 0 , 0
       0     .06       0     516    .045       0     528      .1       0
Bank Sta=516,528
XS Rating Curve= 0 ,0
Exp/Cntr=0.3,0.1

Type RM Length L Ch R = 1 ,2219.2  ,404.7,403.3,402.1
XS GIS Cut Line= 3
     1901907.172      136933.576     1901607.012      136510.643
     1901360.885      136175.906
#Sta/Elev= 30
       0 2223.99    29.9 2214.75    59.8 2207.43    69.8 2205.88    89.8 2210.07
    99.7 2210.88   109.7 2209.16   129.7  2202.5   159.6 2198.93   229.4 2197.09
     379 2196.06   458.8 2193.77   511.3 2190.72   523.3 2190.07   528.5 2189.96
   538.4 2191.74   568.1 2203.59   587.9  2207.7   647.2 2228.38     667 2237.39
   676.9 2240.16   696.7 2250.94   706.6 2254.38   746.2 2286.67   765.9 2298.54
   795.6  2321.9   825.3 2341.26   835.2 2349.04   894.5 2383.95   934.1 2403.25
#Mann= 3 , 0 , 0
       0     .06       0   511.3    .045       0   523.3      .1       0
Bank Sta=511.3,523.3
XS Rating Curve= 0 ,0
Exp/Cntr=0.3,0.1

Type RM Length L Ch R = 1 ,1816    ,371.2,379.6,387.8
XS GIS Cut Line= 3
     1902252.341      136700.018     1902177.933      136590.473
     1901593.571      135886.441
#Sta/Elev= 30
       0 2273.17    18.9 2262.59    37.8 2255.37    47.3 2249.31    75.7 2239.68
   113.5  2215.3   132.4 2207.72   152.3 2203.78   172.2 2202.89   192.1 2204.97
   221.9 2196.05   231.9  2195.6     381 2196.77   609.8 2184.94   611.8 2184.95
   623.8 2185.74   629.7 2186.85   649.6 2198.38   669.5 2205.32   679.4 2206.85
   768.9 2241.28   788.8 2254.94   798.8 2258.22   818.6 2270.88   838.5 2279.94
   908.2 2320.79   987.7 2360.58  1007.6 2366.68  1037.4 2380.05  1047.4  2387.6
#Mann= 3 , 0 , 0
       0     .08       0   611.8    .045       0   623.8      .1       0
Bank Sta=611.8,623.8
XS Rating Curve= 0 ,0
Exp/Cntr=0.3,0.1

Type RM Length L Ch R = 1 ,1436.3  ,387.8,398.1,408.9
XS GIS Cut Line= 3
     1902359.819      136594.607     1902178.375      135995.534
     1902040.938      135610.008
#Sta/Elev= 30
       0 2251.36    19.9 2243.79    49.7 2237.68    89.4 2238.54    99.4  2235.7
   109.3 2229.41   119.2 2228.43   139.1 2212.34     149 2206.48   198.7    2197
   288.1 2193.61   526.6 2191.39   603.8 2183.43   606.1 2183.14   615.8  2183.2
   635.9 2186.19   695.8 2217.89   705.8  2218.4   735.8 2232.42   745.7 2234.27
   755.7 2240.48   795.6 2274.86   835.6 2303.26   845.6 2309.63   855.6 2309.39
   915.4 2353.98   935.4 2366.25   955.4 2371.44   965.4 2376.62  1035.2 2417.36
#Mann= 3 , 0 , 0
       0     .08       0   603.8    .045       0   615.8      .1       0
#XS Ineff= 2 , 0
          335.86  2198.7
Permanent Ineff=
       F       F
Bank Sta=603.8,615.8
XS Rating Curve= 0 ,0
Exp/Cntr=0.3,0.1

Type RM Length L Ch R = 1 ,1038.3  ,494.6,491.1,487.4
XS GIS Cut Line= 3
     1902421.825       136784.76     1902572.008      136003.393
     1902654.983      135602.388
#Sta/Elev= 30
       0 2314.32    19.9 2312.65    99.5 2292.51   119.4 2290.13   139.2 2283.54
   198.9 2251.26   208.9 2251.36   228.8 2237.09   298.4  2203.5     358 2200.35
   397.8 2191.56     726 2191.16   765.8 2188.13   790.3 2182.96   802.3 2182.17
   805.7 2182.06   815.6 2184.13   865.6  2214.8   895.6 2227.37   925.5 2230.81
   935.5 2235.77   995.4 2288.88  1005.4 2296.57  1015.4 2297.92  1065.3 2344.09
  1095.3 2368.74  1105.3 2369.29  1175.2 2418.98  1195.2  2431.8  1205.2  2433.6
#Mann= 3 , 0 , 0
       0     .08       0   790.3    .045       0   802.3      .1       0
Bank Sta=790.3,802.3
XS Rating Curve= 0 ,0
Exp/Cntr=0.3,0.1

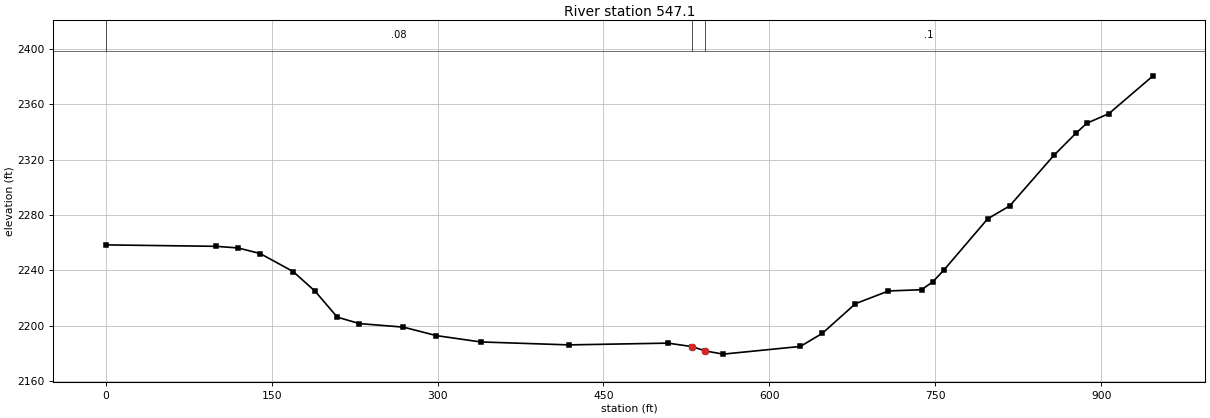
Type RM Length L Ch R = 1 ,547.1   ,555.3,547,539.4
XS GIS Cut Line= 2
     1903043.957      136611.142     1903066.693       135664.51
#Sta/Elev= 30
       0 2258.39    99.7 2257.35   119.6 2256.17   139.5 2252.15   169.4 2239.14
   189.4 2224.79   209.3 2206.21   229.2 2201.56   269.1 2198.98     299 2192.85
   338.9  2188.3   418.6 2186.16   508.3 2187.43     530 2184.93     542 2181.81
   558.2 2179.49     628 2185.04   647.9 2194.52   677.8  2215.9   707.7 2225.11
   737.6 2226.02   747.6 2231.61   757.5 2239.94   797.4 2277.24   817.3 2286.57
   857.2 2323.03   877.1 2338.98   887.1 2346.27     907 2353.21   946.9 2380.49
#Mann= 3 , 0 , 0
       0     .08       0     530    .045       0     542      .1       0
Bank Sta=530,542
XS Rating Curve= 0 ,0
Exp/Cntr=0.3,0.1

Chan Stop Cuts=-1
Use User Specified Reach Order=0
Composite Channel Slope=5